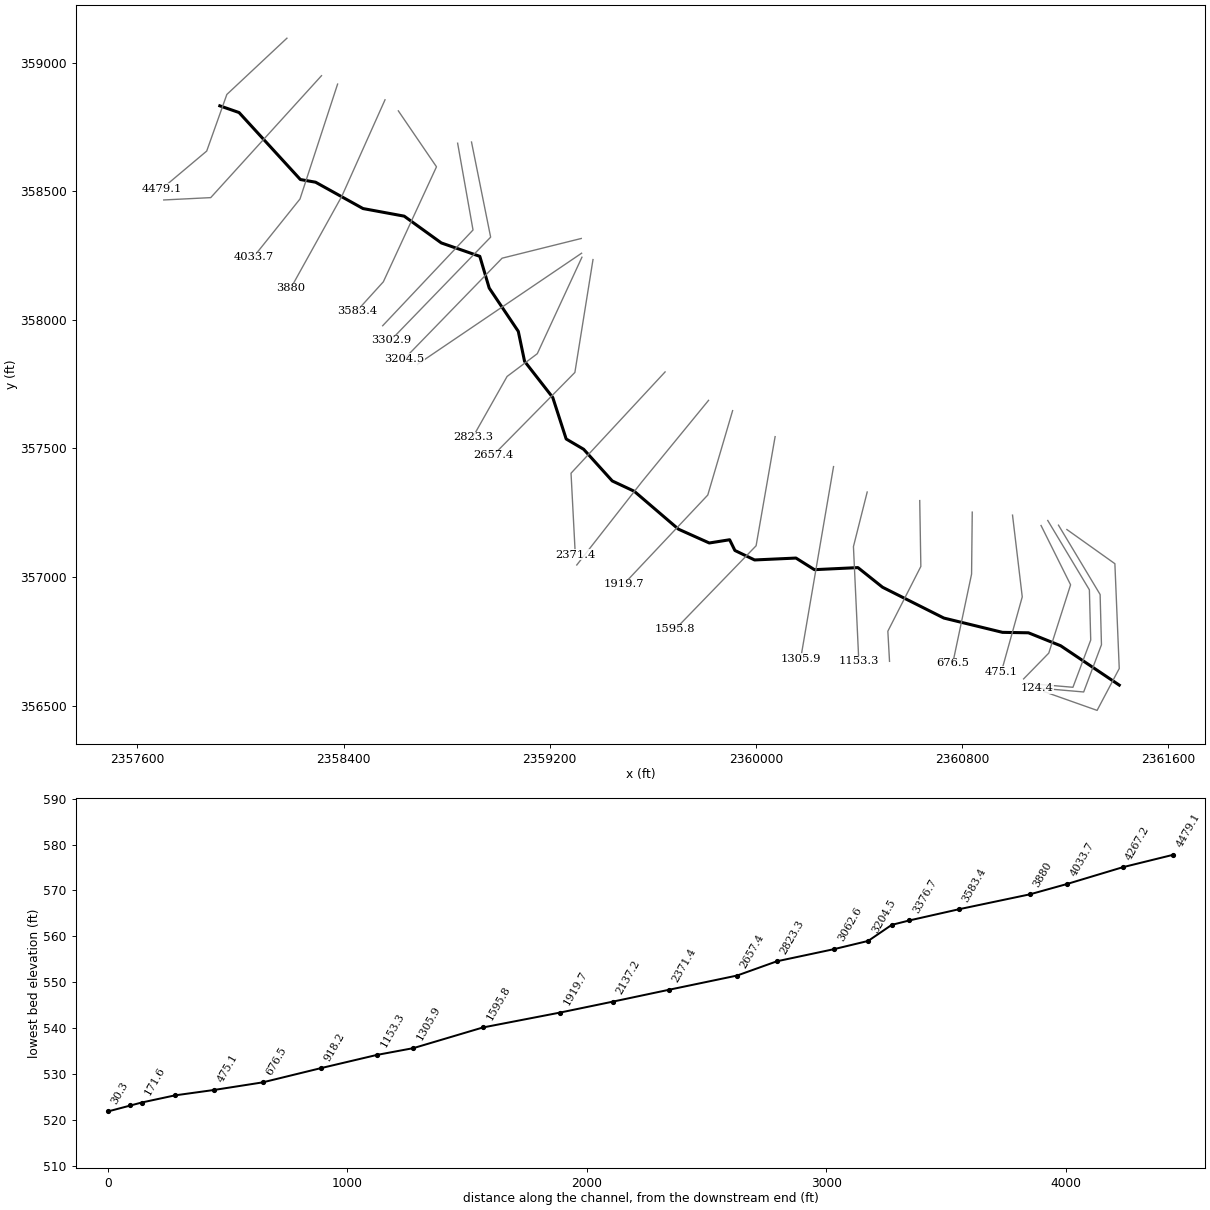
--- ELKBRTRIB1.prj (project) ---

Proj Title=ELKBRTRIB1
Current Plan=p01
Default Exp/Contr=0,0
English Units
Geom File=g01
Flow File=f01
Plan File=p01
BEGIN DESCRIPTION:
END DESCRIPTION:
DSS Export Rating Curves= 0
DSS Export Rating Curve Sorted= 0
DSS Export Volume Flow Curves= 0
DXF OffsetX= 0
DXF OffsetY= 0
DXF ScaleX= 0
DXF ScaleY= 0

--- ELKBRTRIB1.p01 (plan) ---

Plan Title=Floodplain
Program Version=4.00
Geom File=g01
Flow File=f01
K Sum by GR=0
Std Step Tol=0.01
Critical Tol=0.01
Num of Std Step Trials=20
Max Error Tol=0.3
Flow Tol Ratio=0.001
Split Flow NTrial=30
Split Flow Tol=0.02
Split Flow Ratio=0.02
Log Output Level=0
Friction Slope Method=1
Unsteady Friction Slope Method=2
Unsteady Bridges Friction Slope Method=1
Global Log Level=0
CheckData=False
Run HTab=0
Run UNet=0
Run PostProcess=0
UNET Theta=0
UNET Theta Warmup=0
UNET ZTol=0
UNET ZSATol=0
UNET MxIter=0
UNET MaxInSteps=0
UNET DtIC=0
UNET DtMin=0
UNET MaxCRTS=0
UNET WFStab=0
UNET SFStab=0
UNET WFX=0
UNET SFX=0
UNET DSS MLevel=0
UNET DZMax Abort=0
UNET Convert EG Bridges=0
UNET Use Existing IB Tables=0
UNET Froude Limit=0
UNET Froude Power=0
Write IC File=0
Echo Input=False
Echo Output=False
Write Detailed=0

--- ELKBRTRIB1.f01 (steady flow) ---

Flow Title=NFF Regression Equation
Program Version=4.00
Number of Profiles=1
Profile Names=P100yr
River Rch & RM=ELKBRTRIB1,Main      ,4479.1
636.6004
River Rch & RM=ELKBRTRIB1,Main      ,475.1
701.9414
River Rch & RM=ELKBRTRIB1,Main      ,171.6
702.9232
Boundary for River Rch & Prof#=ELKBRTRIB1,Main      ,1
Up Type=0
Dn Type=3
Dn Slope=0.012937

--- ELKBRTRIB1.g01 (geometry) ---

Geom Title=USGS 10m DEM
Program Version=4.10

River Reach=ELKBRTRIB1      ,Main
Reach XY= 30
     2357919.975      358832.053     2357994.628      358806.011
     2358232.475      358545.594     2358291.503      358535.178
     2358475.531      358432.747     2358635.253      358403.233
      2358779.35      358299.067     2358928.656      358246.983
     2358965.114      358123.719     2359077.961      357955.317
     2359102.267      357838.997     2359211.642      357698.372
     2359263.725      357536.914     2359331.433      357496.983
     2359442.544      357373.719     2359527.614      357333.789
     2359699.489      357186.219     2359818.911      357132.578
     2359897.904      357145.165     2359918.304      357103.499
     2359994.693      357066.606     2360155.283      357073.985
     2360226.897      357028.846     2360395.669      357036.914
     2360491.156      356960.525     2360729.003      356840.733
     2360956.433      356785.178     2361057.128      356783.442
     2361182.128      356733.094     2361409.527      356580.055

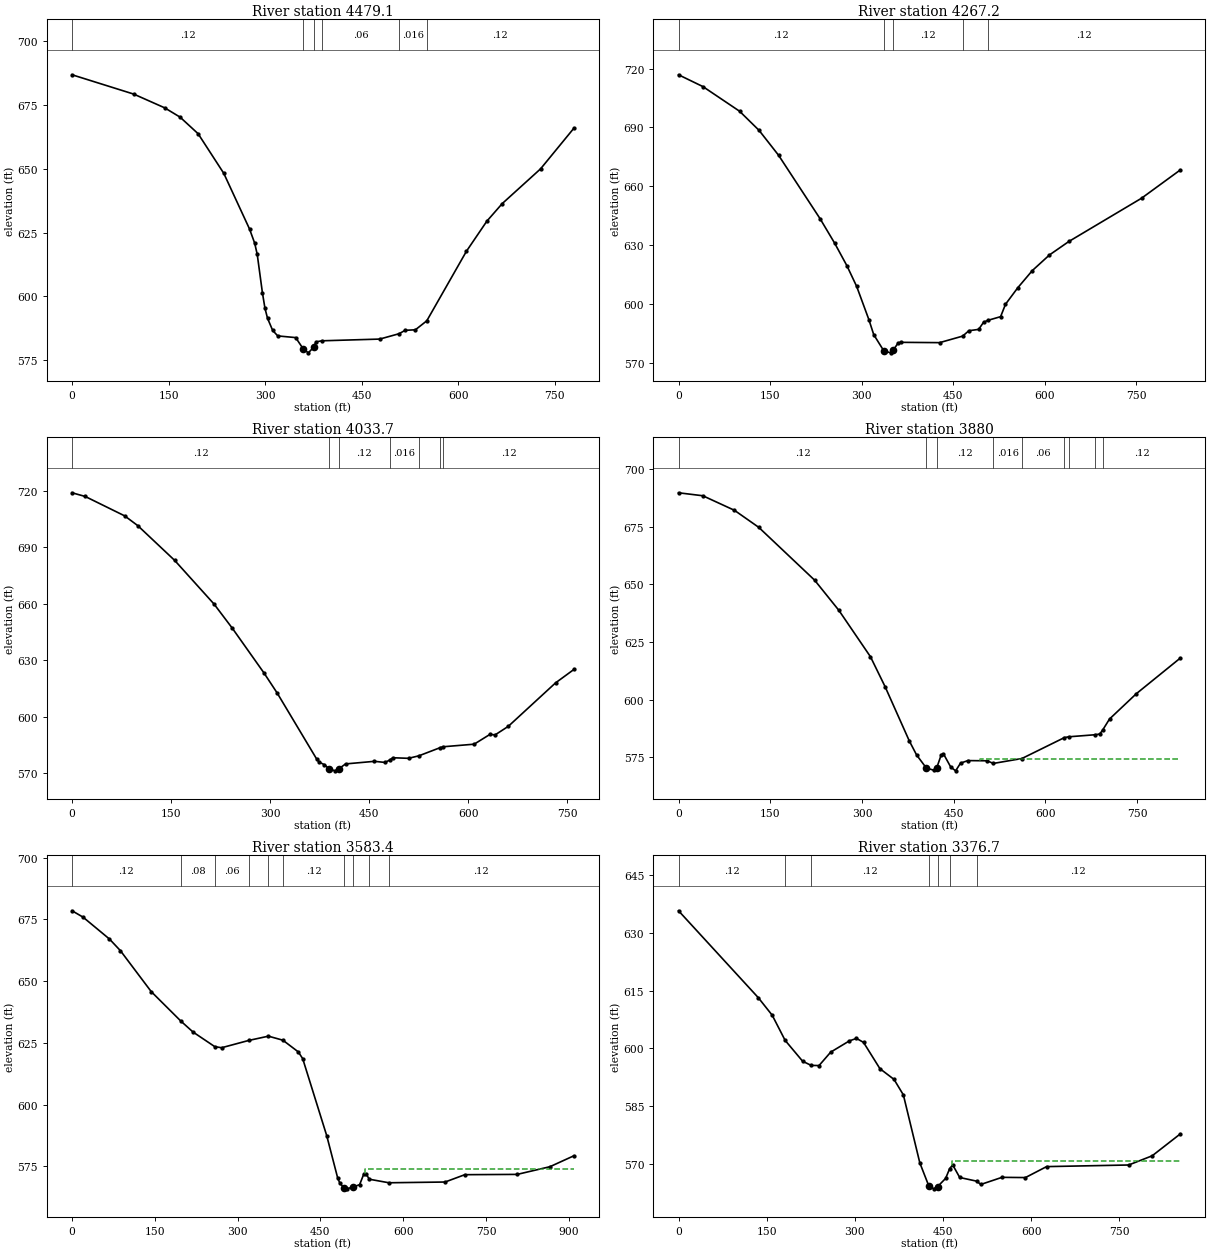
Type RM Length L Ch R = 1 ,4479.1  ,220.9,211.9,202.9
XS GIS Cut Line= 4
     2358180.302      359095.057     2357947.229      358876.307
     2357869.104      358656.255     2357695.927      358510.421
#Sta/Elev= 30
       0  686.89    95.9   679.3   143.8  673.93   167.8  670.27   195.8  663.77
   235.7  648.22   275.7  626.38   283.7  620.83   287.7  616.37   295.7  601.41
   299.7  595.24   303.7  591.32   311.7  586.56   319.6  584.42   347.4  583.76
   359.2  579.31   367.1  577.78   375.1  579.92     379  582.09  388.22582.5031
     478  583.18  508.09585.2848   517.5  586.62   533.4  586.82  551.09590.3405
   612.7  617.64   644.5  629.47   668.3  636.34   727.9  649.98   779.6  665.91
#Mann= 6 ,-1 , 0
       0     .12       0   359.2    .045       0   375.1     .12       0
  388.22     .06       0  508.09    .016       0  551.09     .12       0
Bank Sta=359.2,375.1
XS Rating Curve= 0 ,0
Exp/Cntr=0.3,0.1

Type RM Length L Ch R = 1 ,4267.2  ,223.6,233.4,243.3
XS GIS Cut Line= 3
     2358314.416      358949.223     2357884.729      358475.265
     2357702.437      358466.151
#Sta/Elev= 30
       0  716.86      40  710.83     100  698.28     132  688.51   163.9  675.83
   231.9  643.49   255.9  630.96   275.9  619.49   291.9  608.94   311.9  592.02
   319.9  584.32   336.5  576.02   347.9  575.06   351.5  576.28   359.8  580.08
   363.8  580.42   427.8  580.26  465.56583.5872   475.8  586.34   491.8  587.02
   499.8  590.62  506.83591.6194   527.8  593.51   535.8  599.83   555.8   608.2
   579.8  617.02   607.8  624.97   639.7  631.86   758.8  653.92   822.3  668.34
#Mann= 5 ,-1 , 0
       0     .12       0   336.5    .045       0   351.5     .12       0
  465.56    .016       0  506.83     .12       0
Bank Sta=336.5,351.5
XS Rating Curve= 0 ,0
Exp/Cntr=0.3,0.1

Type RM Length L Ch R = 1 ,4033.7  ,156.2,153.7,149.3
XS GIS Cut Line= 3
     2358376.916      358916.671     2358231.083      358470.057
     2358050.093      358243.494
#Sta/Elev= 30
       0  719.04    19.9  717.08    79.6  706.79    99.5  701.59   155.3  683.16
     215  659.95   242.9     647   290.6  623.37   310.6   612.7   370.3   577.7
   374.3  575.97   382.2  574.66   388.9  572.51   398.2   571.4   403.9  572.47
   414.1  575.07   457.9  576.45   473.8  575.86  481.31 577.194   485.7  578.35
   509.5  578.05  525.15579.3782  557.21 583.691  562.19 584.194   608.8  585.55
   632.7  590.74   640.6   590.5   660.5  595.02     732  618.08   759.8  625.21
#Mann= 7 ,-1 , 0
       0     .12       0   388.9    .045       0   403.9     .12       0
  481.31    .016       0  525.15     .06       0  557.21     .08       0
  562.19     .12       0
Bank Sta=388.9,403.9
XS Rating Curve= 0 ,0
Exp/Cntr=0.3,0.1

Type RM Length L Ch R = 1 ,3880    ,296.5,296.7,298.3
XS GIS Cut Line= 3
     2358560.908      358855.545     2358393.988      358481.962
     2358194.727      358122.125
#Sta/Elev= 30
       0  689.65    39.7  688.36    91.4  682.06   131.1  674.69   222.5  651.79
   262.2   638.7   313.8  618.62   337.7  605.67   377.4   582.1   389.3  576.03
   405.2  570.39   417.2  569.46  422.16  570.46   429.2  575.82   433.1  576.58
   445.1  570.81   453.1  569.17   461.1   572.5   473.1  573.61     505  573.52
  514.54572.3699  561.48574.5079   630.9583.5675  637.84583.9156  681.52 584.817
   688.7  585.12  693.42586.8011   704.7  591.62   748.6   602.6   820.5  618.04
#Mann= 9 ,-1 , 0
       0     .12       0   405.2    .045       0  422.16     .12       0
  514.54    .016       0  561.48     .06       0   630.9     .08       0
  637.84     .12       0  681.52     .06       0  693.42     .12       0
#XS Ineff= 2 , 0
                           492.7          574.15
Permanent Ineff=
       F       F
Bank Sta=405.2,422.16
XS Rating Curve= 0 ,0
Exp/Cntr=0.3,0.1

Type RM Length L Ch R = 1 ,3583.4  ,215,206.6,198.3
XS GIS Cut Line= 4
     2358612.593      358812.505     2358760.597      358595.057
     2358554.434      358148.008     2358451.135      358033.859
#Sta/Elev= 30
       0  678.52    19.9  675.94    67.8  667.07    87.7  662.34   143.5  645.77
  196.94 633.892   219.2  629.42  258.58623.5035     271  623.06  320.07626.0096
  355.83627.7447  382.03626.1091   409.9  621.38   417.9  618.66   461.5  587.42
   481.4  570.24   485.4  568.18   493.3  566.15   497.3  565.92   509.2  566.66
   521.1  567.62     529  572.11     533  571.81   538.8569.8045  574.12568.3787
   675.9  568.68   711.7  571.65   806.6  571.77   865.9  574.88   909.3   579.3
#Mann= 10 ,-1 , 0
       0     .12       0  196.94     .08       0  258.58     .06       0
  320.07     .08       0  355.83     .06       0  382.03     .12       0
   493.3    .045       0   509.2     .12       0   538.8    .016       0
  574.12     .12       0
#XS Ineff= 2 , 0
                          530.44          573.99
Permanent Ineff=
       F       F
Bank Sta=493.3,509.2
XS Rating Curve= 0 ,0
Exp/Cntr=0.3,0.1

Type RM Length L Ch R = 1 ,3376.7  ,73.6,73.9,74
XS GIS Cut Line= 3
     2358842.628      358686.854     2358902.307      358349.397
     2358551.829      357977.218
#Sta/Elev= 30
       0   635.8   135.5  613.24   159.4  608.64  181.37602.1056   211.2  596.67
  225.74595.5897   239.1  595.55     259  599.05   290.9  601.98   302.8  602.61
   314.8  601.58   342.7  594.74   366.7  591.95   382.6  587.92   410.6  570.24
   425.7  564.32   434.6  563.49   440.7  564.05   454.5  566.21  461.34 568.724
   466.5  569.73   478.5  566.44  507.12565.4936   514.4  564.63   550.4  566.48
   590.3  566.42   626.3  569.27     766  569.69     806  572.08   853.9  577.78
#Mann= 7 ,-1 , 0
       0     .12       0  181.37     .06       0  225.74     .12       0
   425.7    .045       0   440.7     .12       0  461.34    .016       0
  507.12     .12       0
#XS Ineff= 2 , 0
                          465.43          570.81
Permanent Ineff=
       F       F
Bank Sta=425.7,440.7
XS Rating Curve= 0 ,0
Exp/Cntr=0.3,0.1

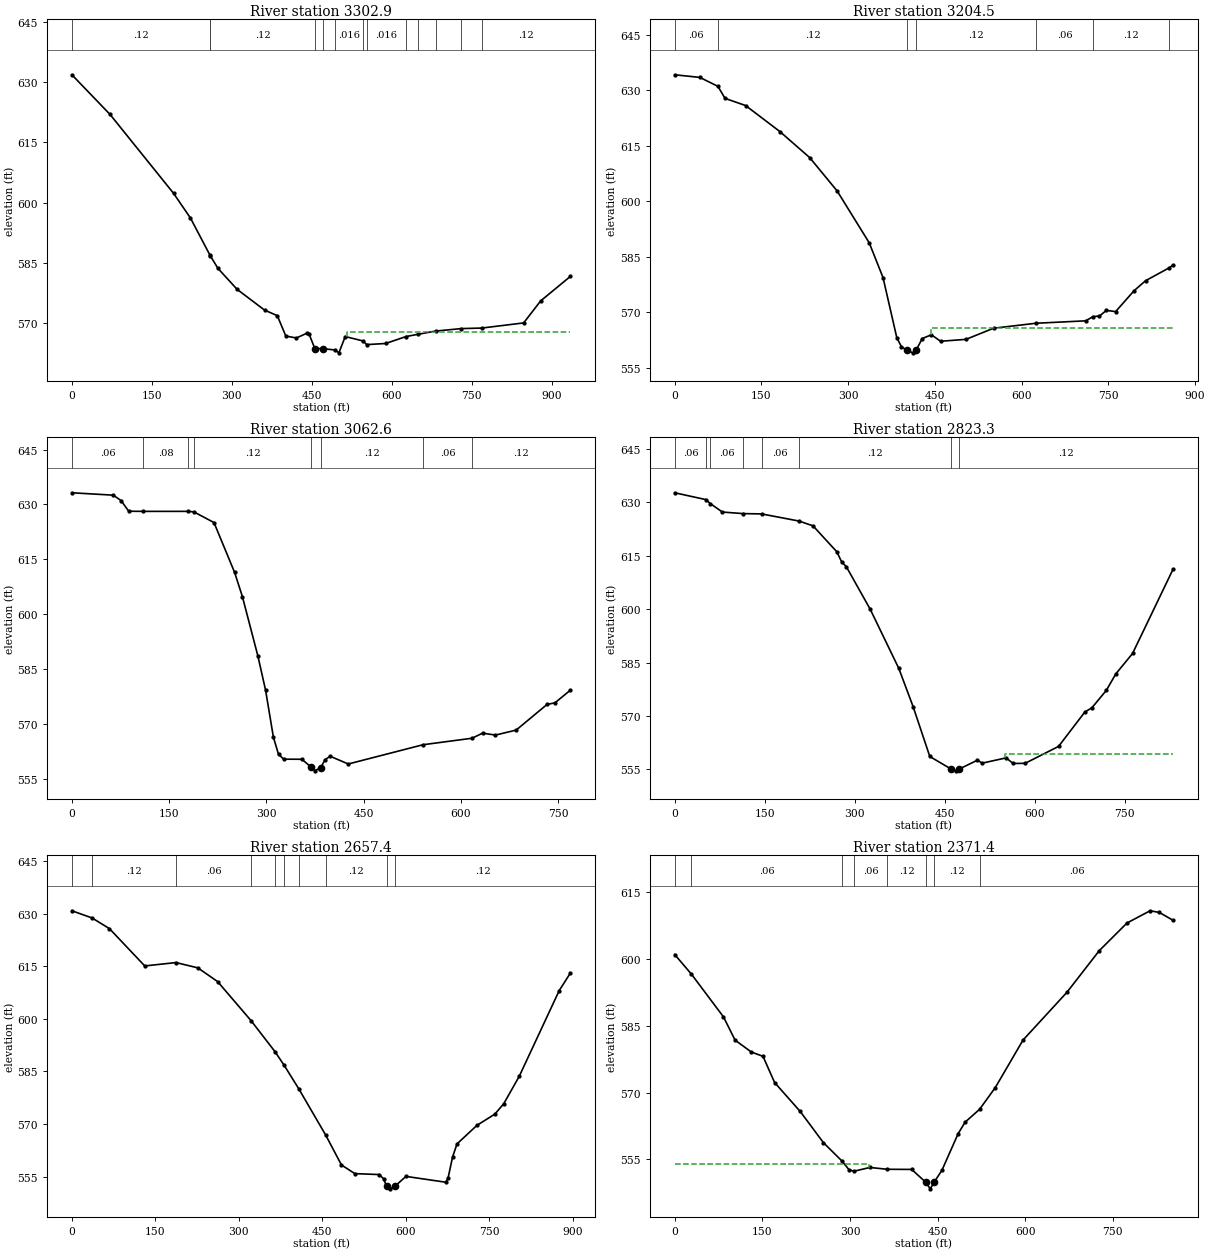
Type RM Length L Ch R = 1 ,3302.9  ,99,98.3,99.7
XS GIS Cut Line= 3
     2358896.448      358691.411     2358970.666      358321.619
     2358583.296      357920.795
#Sta/Elev= 30
       0  631.86    71.5  621.97   190.6   602.3   222.3  596.13  258.36587.0013
  259.19586.7822   273.9  583.57   309.7  578.36   361.3  573.17   385.1   571.8
   401.1   566.7     421  566.23   440.9  567.43   444.8  567.18  455.49  563.57
  470.22  563.58  493.34563.2219   500.6  562.52   512.5  566.59  545.98565.4757
  552.78564.5737   588.2  564.85   626.6566.5885  649.15567.1506  681.88567.9456
  729.96 568.563  768.32568.6989     847  569.98   878.8  575.46   934.6  581.58
#Mann= 13 ,-1 , 0
       0     .12       0  258.36     .06       0  259.19     .12       0
  455.49    .045       0  470.22     .12       0  493.34    .016       0
  545.98     .08       0  552.78    .016       0   626.6     .12       0
  649.15     .08       0  681.88     .12       0  729.96     .08       0
  768.32     .12       0
#XS Ineff= 2 , 0
                             516          567.84
Permanent Ineff=
       F       F
Bank Sta=455.49,470.22
XS Rating Curve= 0 ,0
Exp/Cntr=0.3,0.1

Type RM Length L Ch R = 1 ,3204.5  ,146.5,141.9,135.1
XS GIS Cut Line= 3
     2359322.229      358316.411     2359015.154      358239.805
      2358635.38      357848.095
#Sta/Elev= 30
       0  634.18    43.5  633.47   74.81 631.047      87   627.8   122.6  625.87
     182  618.82   233.4   611.8   280.9  602.78   336.4  588.77   360.3  579.36
   384.2  563.05   392.2  560.67  402.18  559.67   412.1  559.03  417.34  559.67
     428  562.89   443.9  563.91   459.8  562.16   503.7  562.67   551.4  565.68
  624.86567.0272   710.7  567.68   723.4568.8087   734.6  568.98   746.6  570.51
   762.5  570.17   794.4  575.81   814.3  578.52  854.53581.9498   862.1  582.76
#Mann= 7 ,-1 , 0
       0     .06       0   74.81     .12       0  402.18    .045       0
  417.34     .12       0  624.86     .06       0   723.4     .12       0
  854.53    .016       0
#XS Ineff= 2 , 0
                          442.72          565.68
Permanent Ineff=
       F       F
Bank Sta=402.18,417.34
XS Rating Curve= 0 ,0
Exp/Cntr=0.3,0.1

Type RM Length L Ch R = 1 ,3062.6  ,238.5,239.3,240.1
XS GIS Cut Line= 2
     2359323.531      358259.119     2358687.463      357827.479
#Sta/Elev= 30
       0  633.19    63.7  632.54    75.7  631.08    87.6  628.15  109.65628.1107
  179.52628.1152  188.29627.9573   219.1  625.06   250.9  611.44   262.9  604.84
   286.8  588.62   298.7  579.26   310.7  566.47   318.6  561.76   326.6  560.44
   354.5  560.41   368.7  558.32   374.4  557.25   383.7  558.11   390.3  560.28
   398.3  561.23   426.2  559.12  541.47564.3785  616.92566.1492   633.3  567.54
   653.2  567.02   685.1  568.38   732.8   575.4   744.8  575.81   768.7  579.28
#Mann= 8 ,-1 , 0
       0     .06       0  109.65     .08       0  179.52     .06       0
  188.29     .12       0   368.7    .045       0   383.7     .12       0
  541.47     .06       0  616.92     .12       0
Bank Sta=368.7,383.7
XS Rating Curve= 0 ,0
Exp/Cntr=0.3,0.1

Type RM Length L Ch R = 1 ,2823.3  ,162.6,165.9,169.6
XS GIS Cut Line= 4
     2359324.833      358243.494     2359151.656      357868.494
     2359034.468      357779.953     2358901.656      357544.276
#Sta/Elev= 30
       0  632.72   52.19630.7921   59.24629.6902    79.4  627.31  113.53626.8725
  144.74  626.78  207.29624.7687   230.4  623.43   270.1  616.14     278  613.35
     286  611.93   325.7     600   373.3   583.4   397.2  572.63     425  558.63
   460.7  555.08   468.6   554.6  473.87  555.09   504.4   557.6   512.3  556.76
     552  558.24   563.9  556.67   583.8  556.71   639.5  561.46   683.3  571.12
   695.2  572.34   719.1  577.21     735  581.86   762.8  587.57   830.5  611.32
#Mann= 8 ,-1 , 0
       0     .06       0   52.19     .12       0   59.24     .06       0
  113.53     .12       0  144.74     .06       0  207.29     .12       0
   460.7    .045       0  473.87     .12       0
#XS Ineff= 2 , 0
                          551.08          559.43
Permanent Ineff=
       F       F
Bank Sta=460.7,473.87
XS Rating Curve= 0 ,0
Exp/Cntr=0.3,0.1

Type RM Length L Ch R = 1 ,2657.4  ,285.3,286,286.4
XS GIS Cut Line= 3
     2359367.802       358234.38     2359297.489      357795.578
     2358981.083      357473.963
#Sta/Elev= 30
       0  630.79   36.21628.7443    67.4  625.71   130.9  615.06  186.99616.0214
   226.2  614.52   261.9  610.59  321.99 599.437  364.88590.6277  381.58 586.673
  408.08579.8988  455.92566.8492   484.3  558.31   508.3  555.84   552.2  555.57
   560.2  554.34   565.3  552.22   572.2   551.5   580.3  552.21   600.1  555.05
     672  553.38     676   554.7     684   560.6   691.9  564.31   727.9  569.63
   759.8  572.79   775.8  575.75   803.7  583.58   875.6  608.05   895.6  613.04
#Mann= 10 ,-1 , 0
       0     .06       0   36.21     .12       0  186.99     .06       0
  321.99     .12       0  364.88     .06       0  381.58     .12       0
  408.08     .06       0  455.92     .12       0   565.3    .045       0
   580.3     .12       0
Bank Sta=565.3,580.3
XS Rating Curve= 0 ,0
Exp/Cntr=0.3,0.1

Type RM Length L Ch R = 1 ,2371.4  ,232,234.2,236.3
XS GIS Cut Line= 3
     2359647.482      357797.624     2359282.564      357403.789
     2359299.059      357087.803
#Sta/Elev= 30
       0  601.02   28.38596.6531    83.5  587.01   103.4  581.78   131.2  579.12
   151.1  578.16     171  572.27   214.8  565.78   254.5  558.77  285.59554.7314
   298.3   552.7  306.82552.3439   334.1  553.19  363.93552.7851   405.7  552.75
   429.5  549.89   437.5  548.39  444.02  549.88   457.4  552.55   485.2  560.79
   497.1  563.37  521.85566.2487   548.8  571.14   596.2   581.8   671.4  592.54
   726.8   601.9   774.2   608.1   813.8  610.85   829.6  610.48   853.3  608.69
#Mann= 8 ,-1 , 0
       0     .12       0   28.38     .06       0  285.59     .04       0
  306.82     .06       0  363.93     .12       0   429.5    .045       0
  444.02     .12       0  521.85     .06       0
#XS Ineff= 2 , 0
           332.3  554.05
Permanent Ineff=
       F       F
Bank Sta=429.5,444.02
XS Rating Curve= 0 ,0
Exp/Cntr=0.3,0.1

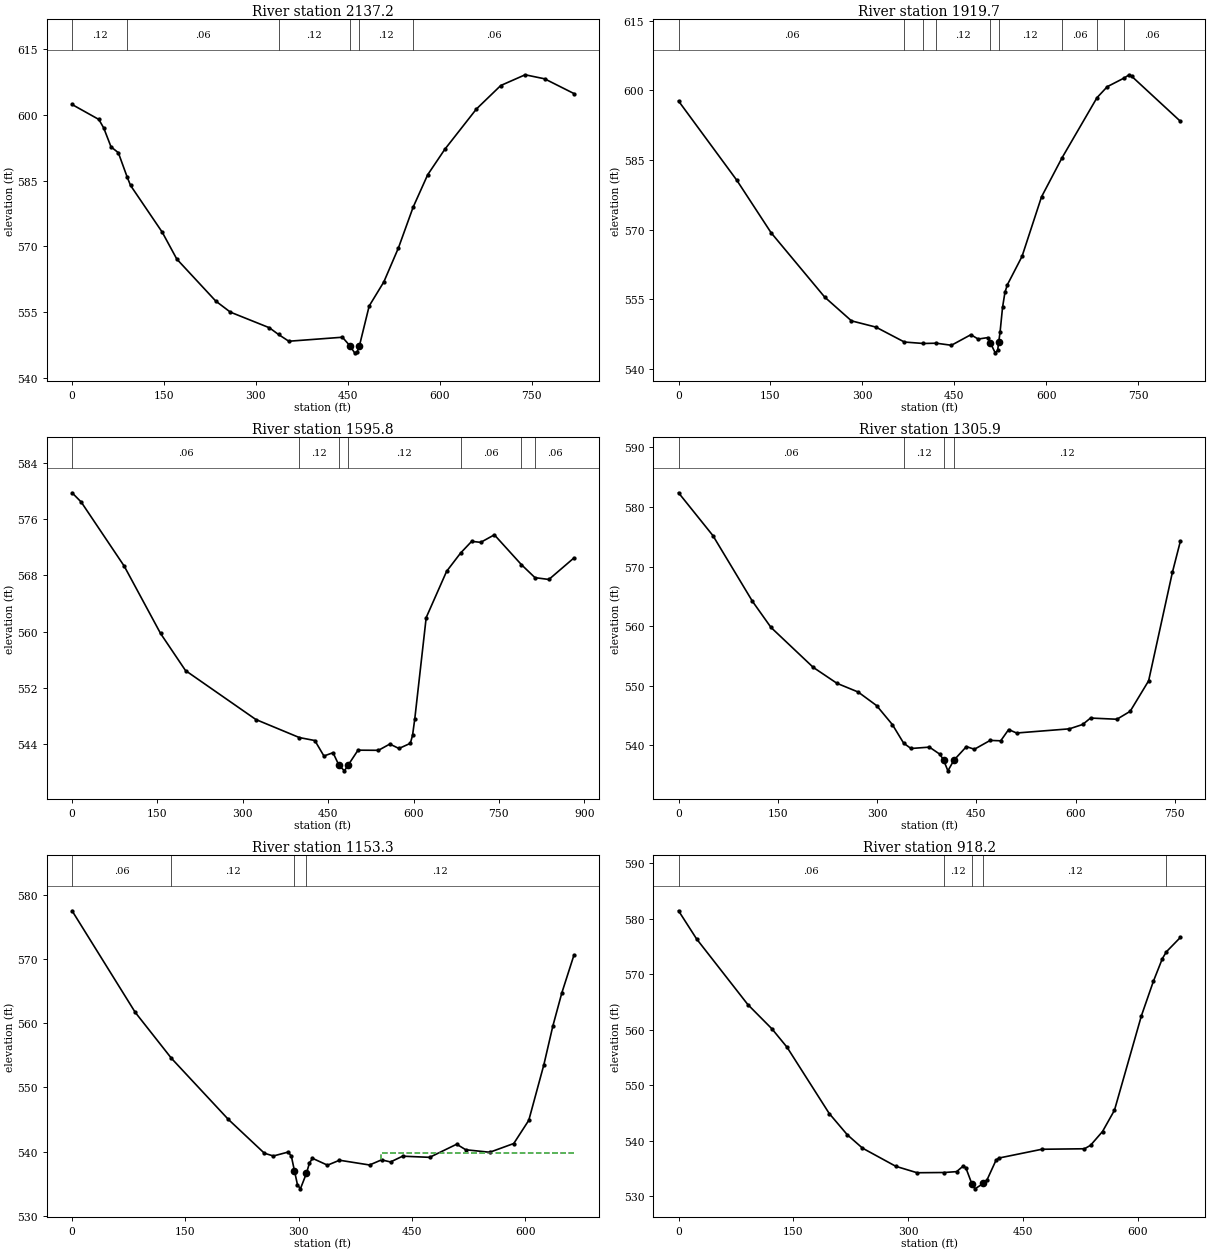
Type RM Length L Ch R = 1 ,2137.2  ,219.6,217.6,215.5
XS GIS Cut Line= 3
     2359816.053      357687.066     2359557.042      357369.912
     2359304.891      357047.102
#Sta/Elev= 30
       0   602.3    43.7   598.9    51.7  596.95    63.6  592.66    75.5  591.34
   89.74585.8766    95.4   583.9   147.1  573.27     171  567.13   234.6  557.58
   258.4  555.07     322  551.52  337.07549.9817   353.8  548.45   441.3  549.36
   453.2  547.47   461.2  545.81   465.2  545.97   469.1  547.43     485  556.47
   508.9  561.94   532.8   569.7  556.79578.9612   580.5  586.32   608.3  592.08
     660  601.27   699.8  606.62   739.6  609.06   771.4  608.14   819.1   604.8
#Mann= 6 ,-1 , 0
       0     .12       0   89.74     .06       0  337.07     .12       0
   453.2    .045       0   469.1     .12       0  556.79     .06       0
Bank Sta=453.2,469.1
XS Rating Curve= 0 ,0
Exp/Cntr=0.3,0.1

Type RM Length L Ch R = 1 ,1919.7  ,323.4,323.9,329.1
XS GIS Cut Line= 3
     2359909.468       357647.14     2359813.114      357319.015
     2359486.291      356971.359
#Sta/Elev= 30
       0  597.73    95.4   580.6   151.1  569.34   238.6  555.47   282.3  550.35
   322.1  549.01  368.69545.7877  399.67545.4766  420.69545.5358   445.4  545.09
   477.2  547.37   489.1  546.43     505  546.75   508.8  545.67   516.9  543.46
   520.9  543.99  522.61  545.76   524.9  547.98   528.9  553.25   532.8  556.49
   536.8  558.14   560.7  564.24   592.5  577.07     626585.4863   683.1598.4508
   699.8  600.81   727.3 602.676   735.6  603.38   739.6  603.07   819.1  593.37
#Mann= 9 ,-1 , 0
       0     .06       0  368.69     .12       0  399.67     .06       0
  420.69     .12       0   508.8    .045       0  522.61     .12       0
     626     .06       0   683.1     .08       0   727.3     .06       0
Bank Sta=508.8,522.61
XS Rating Curve= 0 ,0
Exp/Cntr=0.3,0.1

Type RM Length L Ch R = 1 ,1595.8  ,275.5,289.9,303.8
XS GIS Cut Line= 3
     2360074.337       357545.99     2360000.552      357121.728
     2359686.967      356797.292
#Sta/Elev= 30
       0  579.75      16  578.44    91.7  569.31   155.5  559.74   199.4  554.46
     323   547.5  399.38544.9343   426.6  544.51   442.6  542.31   458.6  542.78
  468.93     541   478.6   540.2  484.87  540.98   502.5  543.14   538.4  543.12
   558.4  544.01   574.4  543.38   594.4  544.11   598.3  545.24   602.3  547.63
   622.3     562   658.2  568.58  682.64571.1673   702.2  572.84   718.1   572.7
   742.1  573.77  789.67569.5238  813.48567.6786   837.9  567.42   881.8  570.47
#Mann= 7 ,-1 , 0
       0     .06       0  399.38     .12       0  468.93    .045       0
  484.87     .12       0  682.64     .06       0  789.67     .12       0
  813.48     .06       0
Bank Sta=468.93,484.87
XS Rating Curve= 0 ,0
Exp/Cntr=0.3,0.1

Type RM Length L Ch R = 1 ,1305.9  ,147.8,152.5,157
XS GIS Cut Line= 2
     2360301.008      357429.598     2360173.404      356682.202
#Sta/Elev= 30
       0  582.38    51.9   575.2   111.7  564.16   139.7  559.78   203.5  553.08
   239.4   550.4   271.4  548.94   299.3  546.66   323.2  543.46  340.14540.3589
   351.2  539.46   379.1  539.69   395.1  538.48  400.58  537.49     407  535.71
  416.17  537.51     435  539.78     447  539.33   470.9  540.82   486.8  540.75
   498.8  542.64   510.8  542.06   590.6  542.76   610.6  543.49   622.5  544.57
   662.4  544.37   682.4   545.7   710.3  550.82   746.2  569.02   758.2  574.22
#Mann= 4 ,-1 , 0
       0     .06       0  340.14     .12       0  400.58    .045       0
  416.17     .12       0
Bank Sta=400.58,416.17
XS Rating Curve= 0 ,0
Exp/Cntr=0.3,0.1

Type RM Length L Ch R = 1 ,1153.3  ,247.2,235.1,222.8
XS GIS Cut Line= 3
     2360431.604      357330.734     2360378.218      357118.494
     2360399.052      356673.182
#Sta/Elev= 30
       0  577.48    83.6  561.69  131.69554.5225   206.9  545.04   254.7  539.77
   266.6  539.34   286.5  539.96   290.5  539.27   294.5  537.06   298.5  534.88
   302.4  534.23   310.4  536.64   314.4  538.24   318.4  538.98   338.3  537.91
   354.2  538.68     394  537.94   409.9  538.74   421.8  538.41   437.8  539.31
   473.6  539.13   509.4  541.17   521.4  540.31   553.2  539.92     585  541.28
   604.9  544.89   624.8   553.5   636.8  559.57   648.7  564.72   664.6  570.54
#Mann= 4 ,-1 , 0
       0     .06       0  131.69     .12       0   294.5    .045       0
   310.4     .12       0
#XS Ineff= 2 , 0
                           409.6           539.8
Permanent Ineff=
       F       F
Bank Sta=294.5,310.4
XS Rating Curve= 0 ,0
Exp/Cntr=0.3,0.1

Type RM Length L Ch R = 1 ,918.2   ,235.8,241.8,247.7
XS GIS Cut Line= 4
       2360635.4      357297.415      2360639.74      357041.339
     2360511.702      356789.602     2360518.213      356672.415
#Sta/Elev= 30
       0  581.44    23.6  576.37    90.6  564.54   122.2  560.15   141.8  556.86
     197  544.91   220.6  541.08   240.4  538.68     284   535.4   311.8  534.24
  347.24534.2827   363.5  534.44   371.5  535.38   375.4  535.18   383.5  532.22
   387.4  531.34   398.5  532.32   403.3  532.97   415.2  536.56   419.2   536.9
   474.9  538.47   530.6  538.56   538.5  539.18   554.2  541.67   569.8   545.5
     605  562.51   620.7  568.74   632.4  572.82  637.71574.0576   655.9  576.63
#Mann= 5 ,-1 , 0
       0     .06       0  347.24     .12       0   383.5    .045       0
   398.5     .12       0  637.71     .06       0
Bank Sta=383.5,398.5
XS Rating Curve= 0 ,0
Exp/Cntr=0.3,0.1

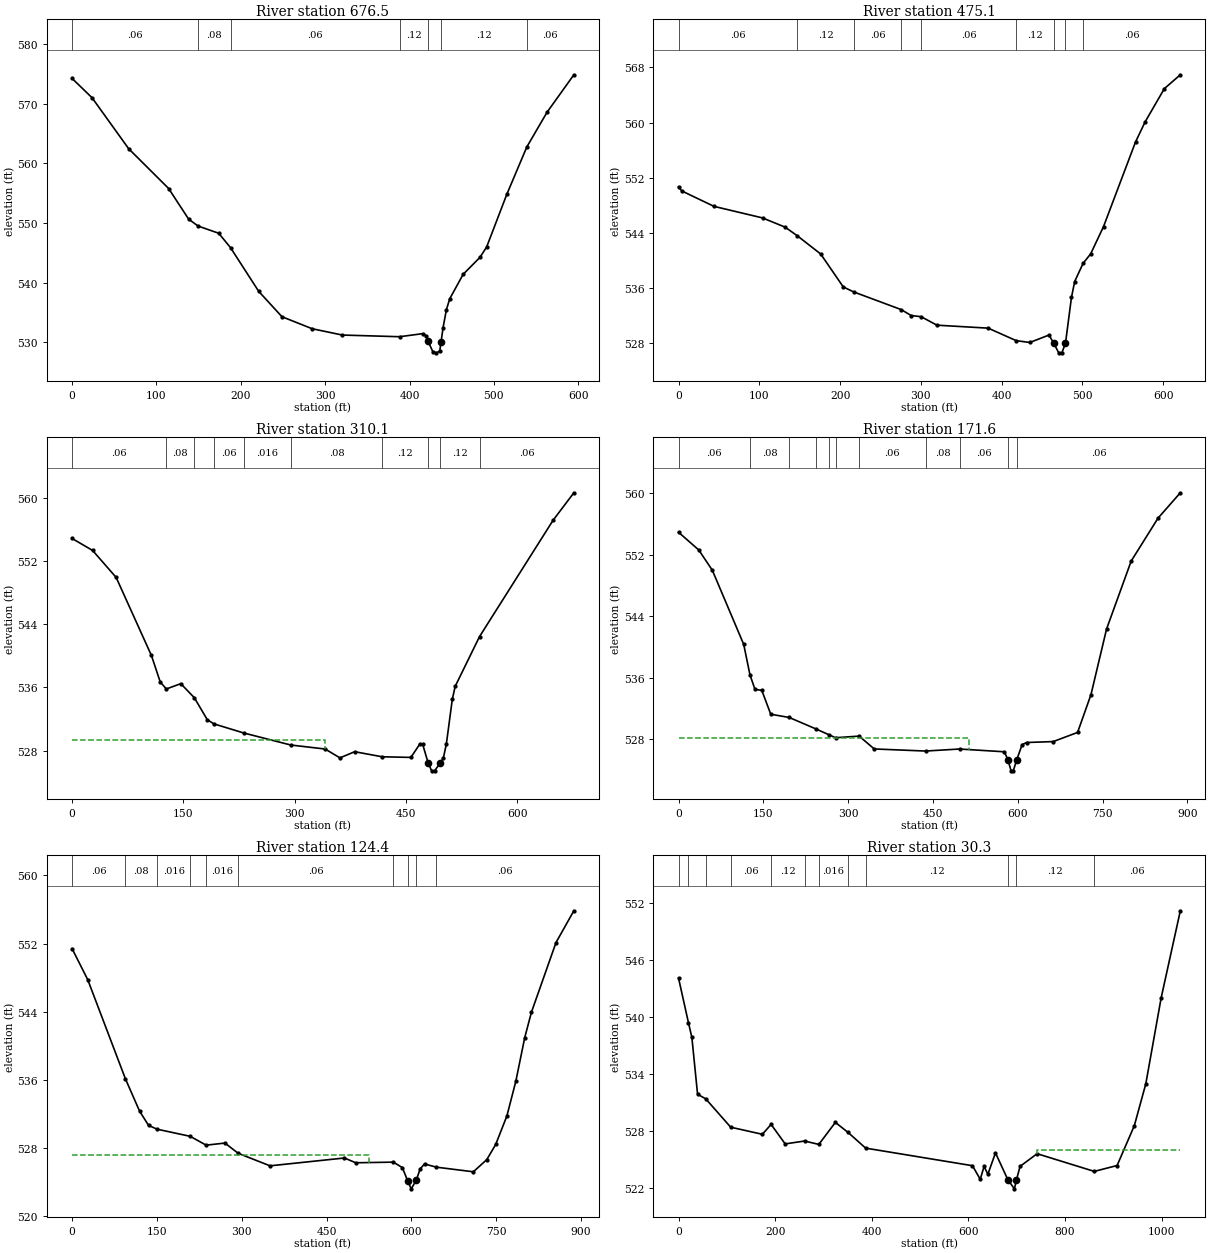
Type RM Length L Ch R = 1 ,676.5   ,202.8,201.3,199.9
XS GIS Cut Line= 3
     2360839.156      357252.609     2360836.552      357011.723
     2360763.635      356665.369
#Sta/Elev= 30
       0  574.24    23.7     571    67.1  562.46   114.5  555.79   138.2  550.66
  149.41549.5014   173.8   548.3  187.85  545.88   221.2  538.57   248.8  534.31
   284.6   532.3   320.4  531.24  388.25530.9606   415.9  531.48   419.9  531.05
  421.67   530.3   427.8   528.4   431.8  528.26   435.8  528.55  437.43  530.14
   439.8   532.5   443.7  535.49   447.7  537.33   463.6  541.42   483.5  544.26
   491.4  545.99   515.3  554.81  538.98562.7406     563  568.57   594.8  574.85
#Mann= 7 ,-1 , 0
       0     .06       0  149.41     .08       0  187.85     .06       0
  388.25     .12       0  421.67    .045       0  437.43     .12       0
  538.98     .06       0
Bank Sta=421.67,437.43
XS Rating Curve= 0 ,0
Exp/Cntr=0.3,0.1

Type RM Length L Ch R = 1 ,475.1   ,166.6,165.1,163.4
XS GIS Cut Line= 3
     2360995.406       357240.89     2361033.166      356923.182
     2360952.437      356632.817
#Sta/Elev= 30
       0  550.68       4  550.09      44  547.85     104  546.18     132  544.84
  146.88543.6052     176  540.95     204  536.17  217.13535.4391  275.82532.8821
     288  532.03  300.42 531.858   319.9  530.63   383.4   530.2  418.06 528.389
   434.9  528.12   458.7   529.2  464.64     528   470.6  526.65   474.6  526.62
  479.08  527.99   486.5  534.65   490.5  536.96  500.89539.5906   510.3  540.97
   526.2  544.92   565.8  557.18   577.7   560.1   601.5  564.92   621.3  566.93
#Mann= 9 ,-1 , 0
       0     .06       0  146.88     .12       0  217.13     .06       0
  275.82     .08       0  300.42     .06       0  418.06     .12       0
  464.64    .045       0  479.08     .12       0  500.89     .06       0
Bank Sta=464.64,479.08
XS Rating Curve= 0 ,0
Exp/Cntr=0.3,0.1

Type RM Length L Ch R = 1 ,310.1   ,139.5,138.4,137.3
XS GIS Cut Line= 4
     2361106.083      357200.526     2361220.666      356970.057
     2361136.031      356704.432     2361038.375      356604.171
#Sta/Elev= 30
       0  554.83    27.7  553.31    59.4   549.9   106.9  540.03   118.8  536.67
     127535.7868   146.5  536.46  164.71534.6812   182.2   531.9  191.16531.3701
  231.19530.2212  294.74528.6962     341  528.19   360.9  527.07   380.8  527.85
  418.01527.2065   456.5  527.13   468.5  528.81   472.4  528.78  479.69  526.46
   484.4  525.44   488.4  525.43   496.3  526.44   500.3  527.06   504.3  528.82
   512.3  534.46   516.2  536.12  549.01542.4152   648.1  557.13   676.1  560.61
#Mann= 10 ,-1 , 0
       0     .06       0     127     .08       0  164.71     .12       0
  191.16     .06       0  231.19    .016       0  294.74     .08       0
  418.01     .12       0  479.69    .045       0   496.3     .12       0
  549.01     .06       0
#XS Ineff= 2 , 0
          340.25  529.39
Permanent Ineff=
       F       F
Bank Sta=479.69,496.3
XS Rating Curve= 0 ,0
Exp/Cntr=0.3,0.1

Type RM Length L Ch R = 1 ,171.6   ,47.1,47.2,47.4
XS GIS Cut Line= 5
     2361132.125      357220.057     2361293.583      356950.526
     2361298.791      356755.213     2361229.781      356571.619
     2361048.791      356587.244
#Sta/Elev= 30
       0  554.95    35.8  552.64    59.7  550.01   115.3  540.34  126.21536.4115
   135.2  534.48   147.2  534.37   163.1  531.25  195.73  530.83  243.42529.3251
  265.24528.6025  277.69528.1931  319.43528.4031   346.1  526.73   436.9 526.458
  496.91526.7221   576.3  526.36  582.68  525.28     588   523.9     592  523.88
  598.14  525.33   607.6  527.29   615.5  527.57   662.6  527.69   705.7  528.88
   729.4  533.81     757  542.36   800.5   551.2   847.9  556.78   887.4  560.09
#Mann= 11 ,-1 , 0
       0     .06       0  126.21     .08       0  195.73    .016       0
  243.42     .06       0  265.24     .08       0  277.69    .016       0
  319.43     .06       0   436.9     .08       0  496.91     .06       0
  582.68    .045       0  598.14     .06       0
#XS Ineff= 2 , 0
          513.93  528.21
Permanent Ineff=
       F       F
Bank Sta=582.68,598.14
XS Rating Curve= 0 ,0
Exp/Cntr=0.3,0.1

Type RM Length L Ch R = 1 ,124.4   ,97.1,94.1,91.1
XS GIS Cut Line= 5
     2361173.791      357201.828      2361335.25      356932.296
     2361340.458      356736.984     2361271.448       356553.39
     2361090.458      356569.015
#Sta/Elev= 30
       0  551.42    27.8  547.76   94.25536.1553   119.3  532.36   135.2  530.68
  150.15530.2322  208.86529.3936  237.05528.3571   270.4   528.6  293.72 527.402
   350.1  525.93   481.7  526.85   501.6  526.29  568.25526.3627   584.1  525.72
  593.74  524.13   599.8  523.23  608.59  524.22   615.5  525.56   623.3  526.15
  644.13525.7746   709.7  525.23   733.4  526.66   749.2  528.44   768.9  531.77
   784.7  535.83   800.5  540.97   812.3  543.94   855.8  552.13   887.4  555.86
#Mann= 10 ,-1 , 0
       0     .06       0   94.25     .08       0  150.15    .016       0
  208.86     .06       0  237.05    .016       0  293.72     .06       0
  568.25     .12       0  593.74    .045       0  608.59     .12       0
  644.13     .06       0
#XS Ineff= 2 , 0
          525.28  527.23
Permanent Ineff=
       F       F
Bank Sta=593.74,608.59
XS Rating Curve= 0 ,0
Exp/Cntr=0.3,0.1

Type RM Length L Ch R = 1 ,30.3    ,29.6,30.3,30.9
XS GIS Cut Line= 5
     2361206.343      357184.901     2361392.541      357052.088
     2361409.468      356644.536     2361323.531      356481.776
     2361117.802      356554.692
#Sta/Elev= 30
       0  544.07   20.57539.3729    27.6  537.84    39.4  531.87   56.41531.3804
  107.99528.4056   173.5  527.66  191.67528.6953   220.8  526.65  260.87526.9524
  290.44526.5978   324.7  528.91  350.72527.8677  387.35526.2072   608.6  524.36
   624.6  522.93   632.6  524.28   640.5  523.47   656.2  525.71  681.77  522.89
   695.4  521.93   699.3  522.81   707.1  524.29   742.4  525.62  860.68523.7636
     908  524.38   943.7  528.57   967.5  532.98   999.2  541.99  1038.9  551.14
#Mann= 12 ,-1 , 0
       0     .06       0   20.57     .08       0   56.41    .016       0
  107.99     .06       0  191.67     .12       0  260.87     .06       0
  290.44    .016       0  350.72     .06       0  387.35     .12       0
  681.77    .045       0   699.3     .12       0  860.68     .06       0
#XS Ineff= 2 , 0
                           741.8          526.03
Permanent Ineff=
       F       F
Bank Sta=681.77,699.3
XS Rating Curve= 0 ,0
Exp/Cntr=0.3,0.1

Chan Stop Cuts=-1
Use User Specified Reach Order=0
Composite Channel Slope=5